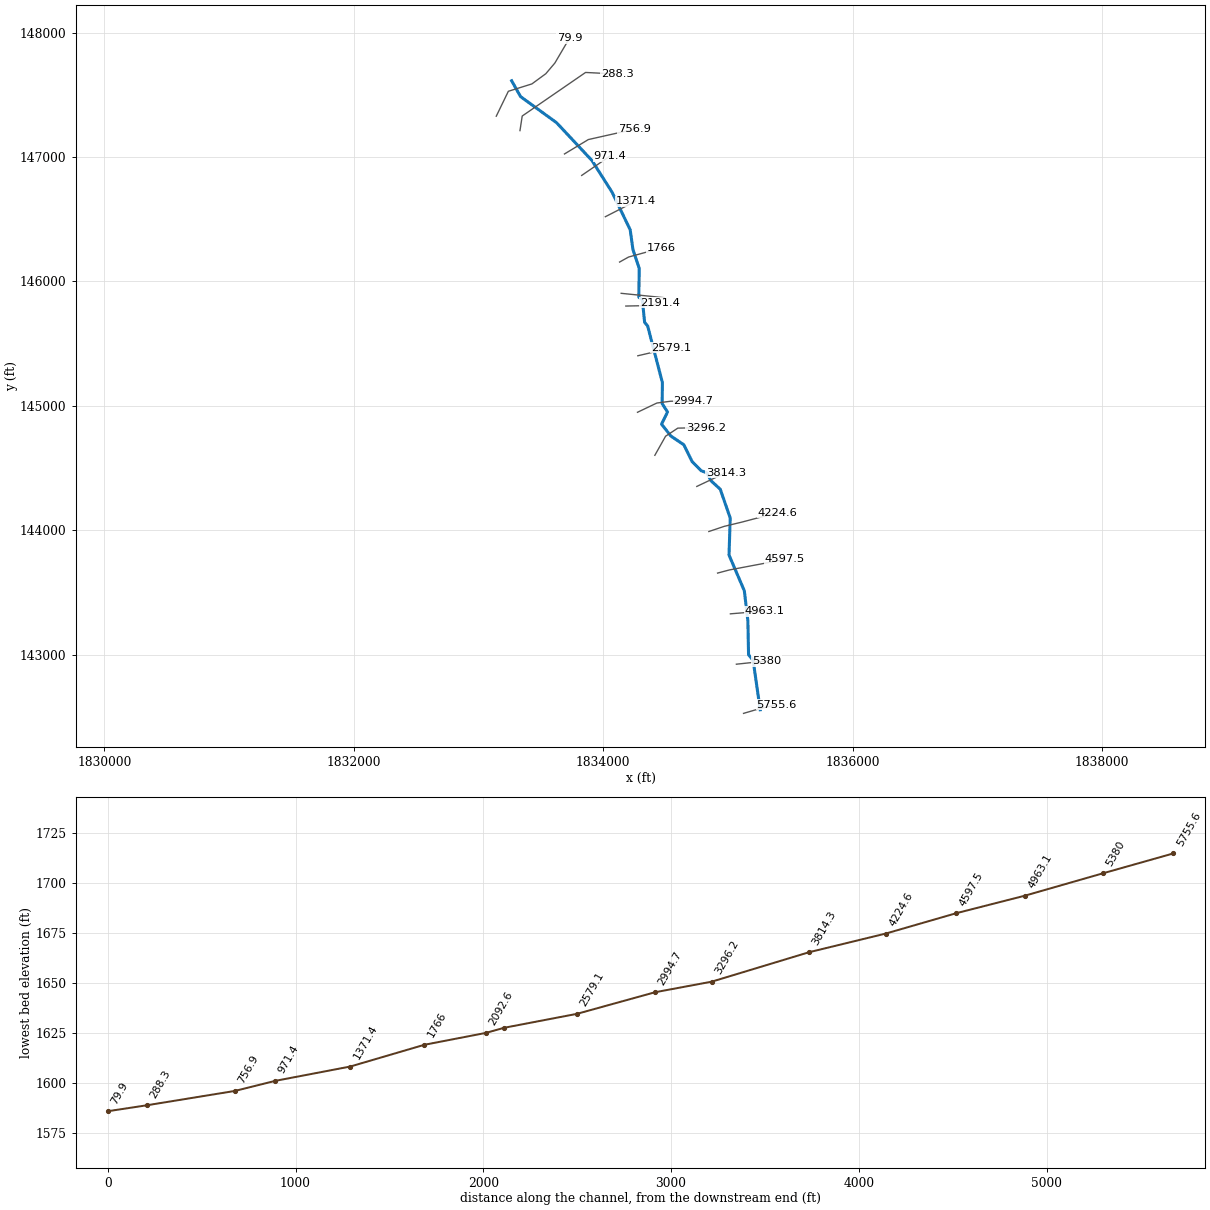
--- Coalbank Branch.prj (project) ---

Proj Title=Coalbank Branch
Current Plan=p01
Default Exp/Contr=0,0
English Units
Geom File=g01
Flow File=f01
Plan File=p01
BEGIN DESCRIPTION:
END DESCRIPTION:
DSS Export Rating Curves= 0
DSS Export Rating Curve Sorted= 0
DSS Export Volume Flow Curves= 0
DXF OffsetX= 0
DXF OffsetY= 0
DXF ScaleX= 0
DXF ScaleY= 0

--- Coalbank Branch.p01 (plan) ---

Plan Title=Floodplain
Program Version=4.00
Geom File=g01
Flow File=f01
K Sum by GR=0
Std Step Tol=0.01
Critical Tol=0.01
Num of Std Step Trials=20
Max Error Tol=0.3
Flow Tol Ratio=0.001
Split Flow NTrial=30
Split Flow Tol=0.02
Split Flow Ratio=0.02
Log Output Level=0
Friction Slope Method=1
Unsteady Friction Slope Method=2
Unsteady Bridges Friction Slope Method=1
Global Log Level=0
CheckData=False
Run HTab=0
Run UNet=0
Run PostProcess=0
UNET Theta=0
UNET Theta Warmup=0
UNET ZTol=0
UNET ZSATol=0
UNET MxIter=0
UNET MaxInSteps=0
UNET DtIC=0
UNET DtMin=0
UNET MaxCRTS=0
UNET WFStab=0
UNET SFStab=0
UNET WFX=0
UNET SFX=0
UNET DSS MLevel=0
UNET DZMax Abort=0
UNET Convert EG Bridges=0
UNET Use Existing IB Tables=0
UNET Froude Limit=0
UNET Froude Power=0
Write IC File=0
Echo Input=False
Echo Output=False
Write Detailed=0

--- Coalbank Branch.f01 (steady flow) ---

Flow Title=NFF Regression Equation
Program Version=4.00
Number of Profiles=1
Profile Names=P100yr
River Rch & RM=Coalbank Branch,Main      ,5755.6
660.6690
River Rch & RM=Coalbank Branch,Main      ,4224.6
679.8237
River Rch & RM=Coalbank Branch,Main      ,3814.3
1028.460
River Rch & RM=Coalbank Branch,Main      ,3296.2
1041.369
River Rch & RM=Coalbank Branch,Main      ,2994.7
1216.538
River Rch & RM=Coalbank Branch,Main      ,288.3
1293.036
Boundary for River Rch & Prof#=Coalbank Branch,Main      ,1
Up Type=0
Dn Type=3
Dn Slope=0.017717

--- Coalbank Branch.g01 (geometry) ---

Geom Title=Geometry
Program Version=4.00

River Reach=Coalbank Branch ,Main
Reach XY= 30
     1835258.463      142558.688     1835201.568      142955.954
     1835164.974       143000.62     1835159.553      143272.287
     1835131.139      143514.622     1835008.248      143801.861
     1835018.053      144099.323     1834937.994      144330.671
     1834863.233      144399.545     1834830.856      144462.533
      1834784.94      144479.604     1834712.196        144553.2
     1834646.013      144687.994     1834542.996      144757.457
     1834467.057       144853.41     1834515.329      144951.718
     1834472.156      145018.388     1834474.122      145187.187
     1834356.073      145641.685     1834331.663      145671.663
     1834313.353      145851.052     1834284.957      145873.769
     1834288.497      146105.053     1834238.065      146256.213
     1834215.695      146415.743     1834072.059      146714.787
     1833909.463      146971.727     1833625.005      147276.396
     1833336.888      147485.491     1833265.335      147612.577

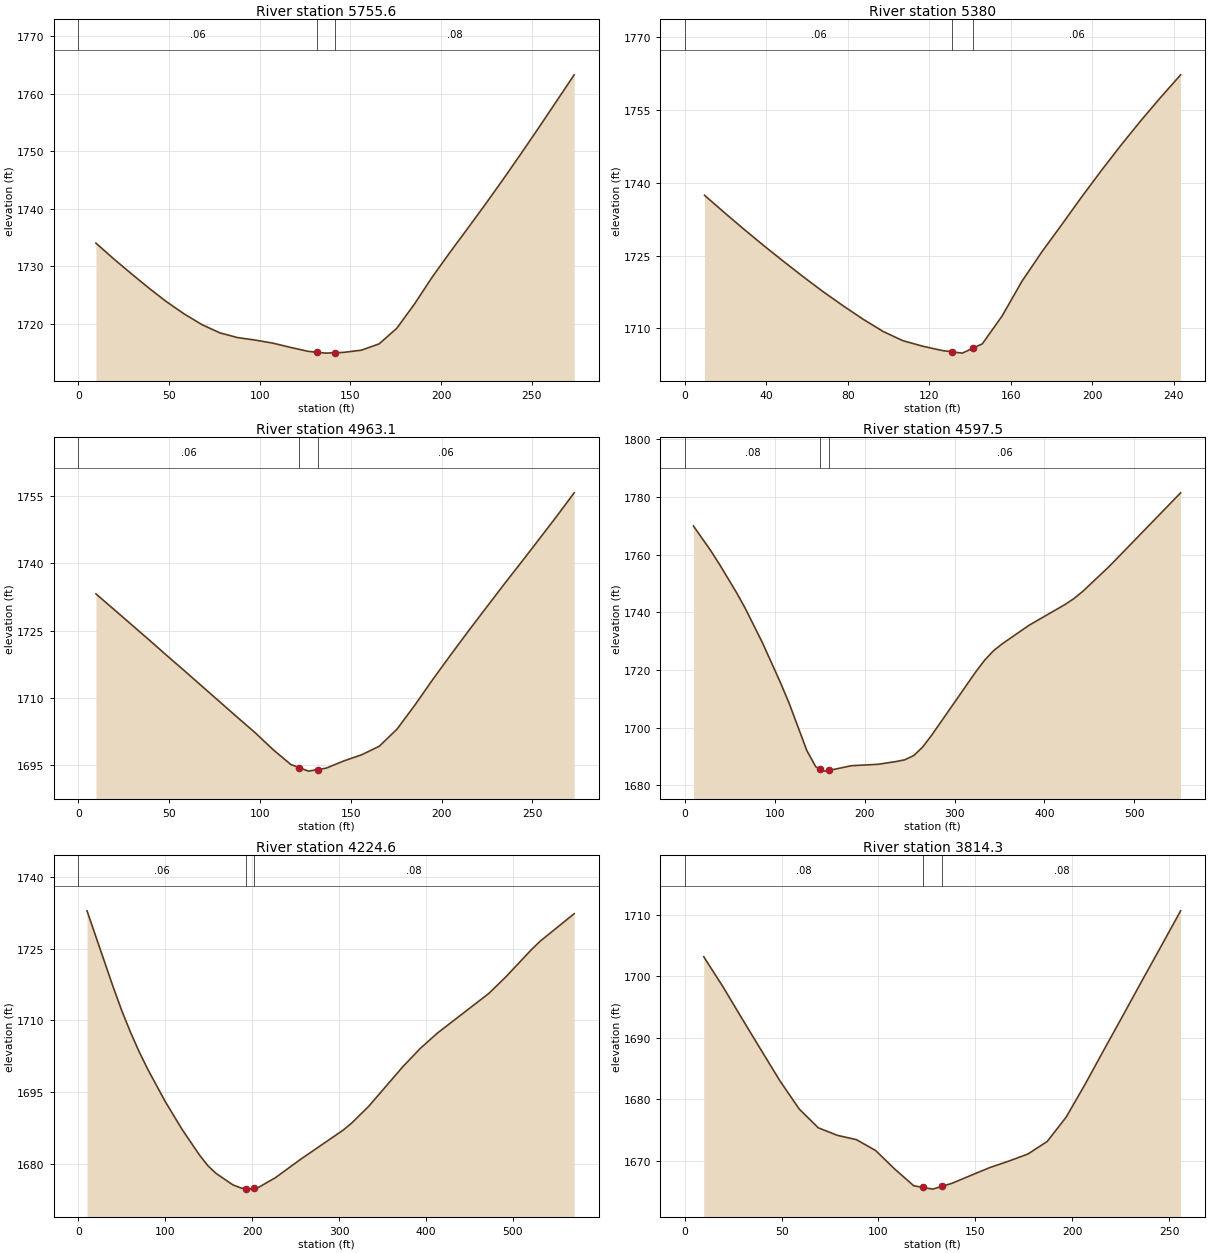
Type RM Length L Ch R = 1 ,5755.6  ,379.2,375.6,373.3
XS GIS Cut Line= 3
     1835124.752      142529.783     1835255.642      142568.282
      1835389.24      142598.036
#Sta/Elev= 30
     9.7 1734.05    19.5 1731.31    29.2 1728.74      39  1726.2    48.7 1723.83
    58.5  1721.7    68.2 1719.86      78 1718.44    87.7 1717.62    97.5 1717.18
   107.2 1716.65   116.9 1715.91   126.7 1715.22   131.4 1715.07   136.4 1714.91
   141.4 1714.98   146.2 1715.04     156 1715.42   165.8 1716.52   175.5 1719.22
   185.3 1723.46   195.1 1728.16   204.9 1732.47   214.6  1736.6   224.4 1740.83
   234.2 1745.16     244 1749.61   253.8 1754.14   263.5  1758.7   273.3 1763.33
#Mann= 3 , 0 , 0
       0     .06       0   131.4    .045       0   141.4     .08       0
Bank Sta=131.4,141.4
XS Rating Curve= 0 ,0
Exp/Cntr=0.3,0.1

Type RM Length L Ch R = 1 ,5380    ,417.4,417,416.5
XS GIS Cut Line= 2
     1835067.311      142924.897     1835309.216      142950.857
#Sta/Elev= 27
     9.7 1737.39    19.5 1733.81    29.2 1730.35    38.9 1726.99    48.7 1723.72
    58.4 1720.55    68.1  1717.5    77.9 1714.61    87.6 1711.88    97.3 1709.39
     107 1707.49   116.8 1706.35   126.5 1705.45   131.2  1705.2   136.2 1704.93
   141.2 1705.91     146 1706.84   155.7 1712.57   165.4 1719.68   175.2 1725.75
   184.9 1731.31   194.6 1736.97   204.4 1742.48   214.1 1747.73   223.8 1752.75
   233.6 1757.58   243.3 1762.17
#Mann= 3 , 0 , 0
       0     .06       0   131.2    .045       0   141.2     .06       0
Bank Sta=131.2,141.2
XS Rating Curve= 0 ,0
Exp/Cntr=0.3,0.1

Type RM Length L Ch R = 1 ,4963.1  ,363.5,365.6,367.7
XS GIS Cut Line= 3
     1835019.337      143329.595     1835155.349      143340.965
     1835291.475       143351.65
#Sta/Elev= 30
     9.7 1733.21    19.5 1729.79    29.2 1726.38      39 1722.94    48.7 1719.47
    58.5 1716.04    68.2 1712.58      78 1709.09    87.7 1705.64    97.5  1702.2
   107.2 1698.49     117 1695.16   121.7 1694.44   126.7 1693.68   131.7 1694.02
   136.5 1694.35   146.2 1695.96     156 1697.33   165.7 1699.23   175.5 1703.06
   185.3 1708.41     195 1714.03   204.8 1719.49   214.5 1724.77   224.3 1729.99
     234 1735.13   243.8 1740.21   253.5  1745.3   263.3 1750.47     273 1755.75
#Mann= 3 , 0 , 0
       0     .06       0   121.7    .045       0   131.7     .06       0
Bank Sta=121.7,131.7
XS Rating Curve= 0 ,0
Exp/Cntr=0.3,0.1

Type RM Length L Ch R = 1 ,4597.5  ,371.9,372.9,374
XS GIS Cut Line= 3
     1834916.563      143657.078      1835009.49       143681.88
     1835456.718      143766.842
#Sta/Elev= 30
     9.6 1769.99    28.9  1761.4    38.5 1756.73    57.7 1746.77    67.3 1741.35
    86.6 1729.29   106.1 1715.81     116 1708.49   135.8 1691.98   145.7  1686.4
   150.6 1685.66   155.6  1684.9   160.6 1685.15   185.2 1686.78   214.9 1687.27
   234.7 1688.21   244.6 1688.83   254.5 1690.29   264.4 1693.21   274.3 1697.26
   323.8 1719.45   333.7 1723.49   343.6 1726.76   353.5  1729.2   383.2 1735.59
   422.8 1742.72   432.7 1744.78   442.5 1747.27   472.2 1756.01   551.4 1781.49
#Mann= 3 , 0 , 0
       0     .08       0   150.6    .045       0   160.6     .06       0
Bank Sta=150.6,160.6
XS Rating Curve= 0 ,0
Exp/Cntr=0.3,0.1

Type RM Length L Ch R = 1 ,4224.6  ,405.8,410.3,414.7
XS GIS Cut Line= 4
     1834846.647      143991.046      1834969.37      144032.346
     1835110.972      144066.567     1835396.537      144142.088
#Sta/Elev= 30
      10 1732.87    39.8 1717.12    49.8 1712.11    59.8 1707.62    69.7 1703.56
    79.7 1699.86    99.6 1693.17   119.5  1687.2   139.2 1681.93   148.9 1679.68
   158.6 1678.02     178 1675.63   187.8 1674.96   192.5 1674.86   197.5 1674.76
   202.5 1674.94   207.2 1675.11   226.6 1677.13   255.7 1680.98   304.7 1687.08
   314.5 1688.55   334.2 1692.07   373.6 1700.37   393.3 1704.11     413 1707.32
   472.1 1715.59   491.8 1719.06   521.3 1724.76   531.2  1726.5   570.5 1732.27
#Mann= 3 , 0 , 0
       0     .06       0   192.5    .045       0   202.5     .08       0
Bank Sta=192.5,202.5
XS Rating Curve= 0 ,0
Exp/Cntr=0.3,0.1

Type RM Length L Ch R = 1 ,3814.3  ,514.8,518.1,521.4
XS GIS Cut Line= 2
     1834749.886      144353.312      1834981.17      144463.054
#Sta/Elev= 28
     9.8 1703.16    19.7 1698.29    29.5 1693.13    39.4 1687.99    49.2 1682.94
    59.1 1678.39    68.9 1675.34    78.8 1674.11    88.6 1673.41    98.5 1671.65
   108.3 1668.65   118.2 1665.91     123 1665.64     128 1665.36     133 1665.83
   137.8 1666.29   147.7 1667.59   157.5 1668.87   167.4 1669.93   177.2 1671.08
   187.1 1673.11   196.9 1677.07   206.8 1682.49   216.6 1688.13   226.5 1693.77
   236.3 1699.41   246.2 1705.03     256 1710.64
#Mann= 3 , 0 , 0
       0     .08       0     123    .045       0     133     .08       0
Bank Sta=123,133
XS Rating Curve= 0 ,0
Exp/Cntr=0.3,0.1

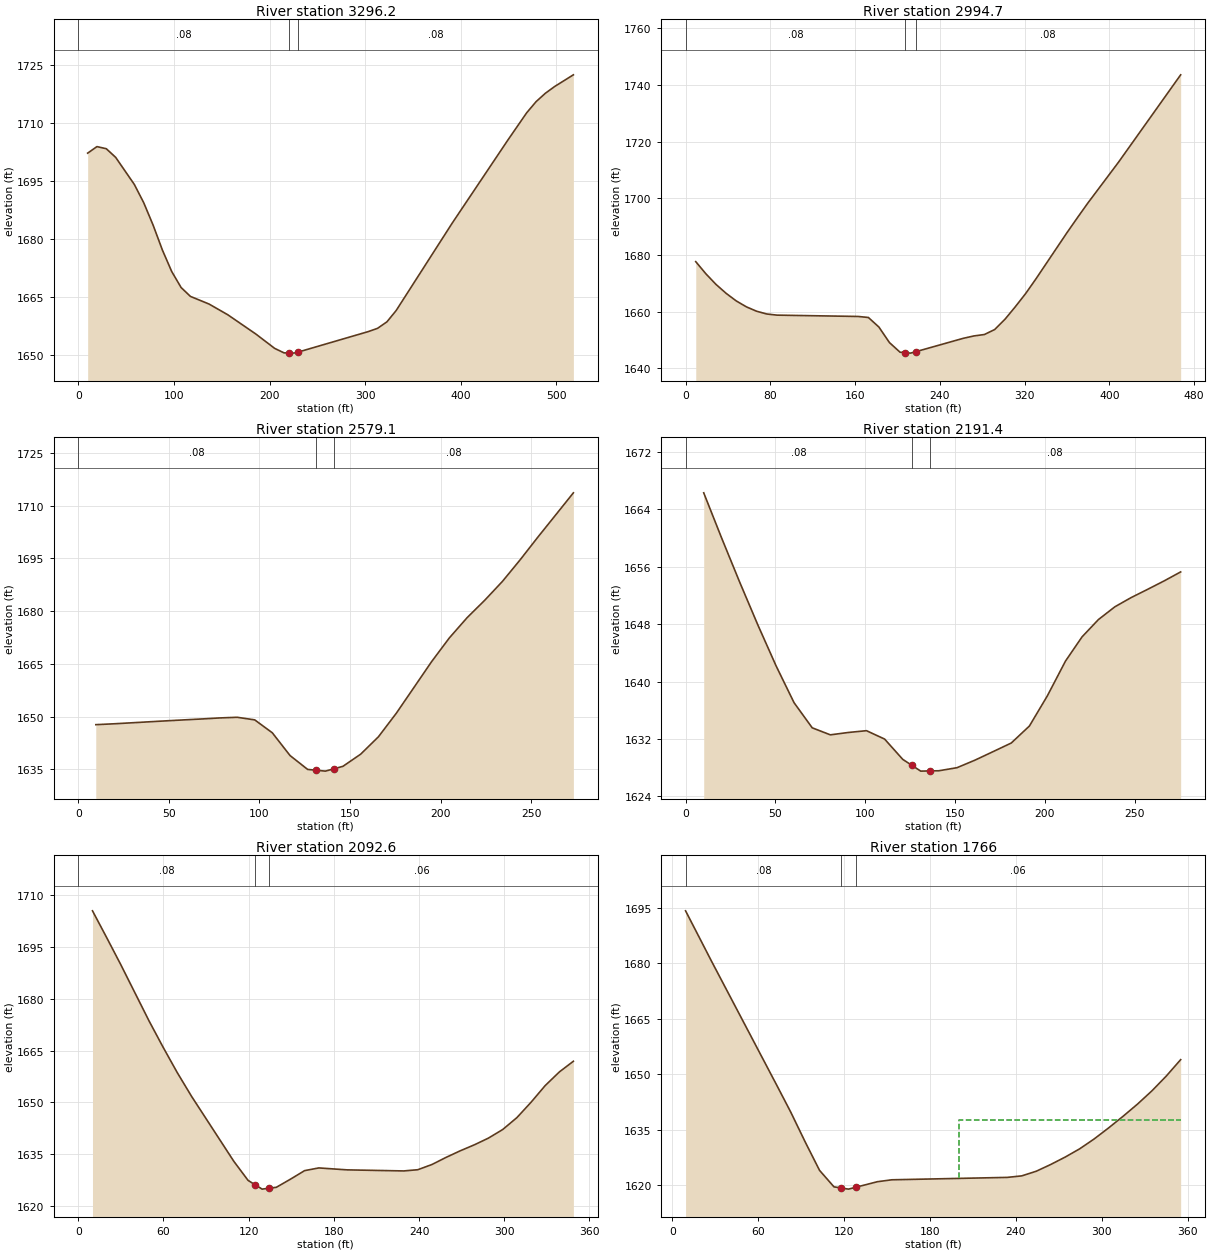
Type RM Length L Ch R = 1 ,3296.2  ,310.9,301.5,291.9
XS GIS Cut Line= 4
      1834413.58      144603.476     1834499.721      144756.879
     1834597.663       144821.78     1834821.867        144826.5
#Sta/Elev= 30
     9.8 1702.18    19.5 1703.87    29.3 1703.32    39.1 1701.09    58.6 1694.11
    68.4 1689.41    78.2 1683.64      88 1677.16    97.7 1671.65   107.5 1667.53
   117.3 1665.23   136.8 1663.26   156.4 1660.49   185.7 1655.53   205.3 1651.84
   215.1 1650.68   219.9 1650.64   224.9 1650.61   229.9 1650.88   303.2 1656.16
   312.9    1657   322.7 1658.67   332.4  1661.6   390.9  1684.1   449.4 1705.63
   468.9  1712.6   478.7 1715.46   488.4 1717.62   498.2 1719.38   517.7 1722.38
#Mann= 3 , 0 , 0
       0     .08       0   219.9    .045       0   229.9     .08       0
Bank Sta=219.9,229.9
XS Rating Curve= 0 ,0
Exp/Cntr=0.3,0.1

Type RM Length L Ch R = 1 ,2994.7  ,413.5,415.6,417.8
XS GIS Cut Line= 4
     1834274.337      144949.222       1834430.1      145023.564
     1834538.662      145037.724     1834723.925      145042.444
#Sta/Elev= 30
     9.6 1677.61    19.2 1673.31    28.8 1669.55    38.4 1666.39    47.9 1663.73
    57.5 1661.64    67.1  1660.1    76.7 1659.13    86.3 1658.73     163 1658.26
   172.6  1657.9   182.5 1654.53   192.5 1649.03   202.5 1645.64   207.4 1645.48
   212.4 1645.32   217.4 1645.83   262.2 1650.55   272.1 1651.38   282.1 1651.89
   291.8 1653.64   301.6  1657.3   311.3 1661.68   321.1 1666.37   330.8 1671.54
   360.1 1687.85   369.9  1693.1   379.6  1698.2   408.9  1712.8   467.4 1743.55
#Mann= 3 , 0 , 0
       0     .08       0   207.4    .045       0   217.4     .08       0
Bank Sta=207.4,217.4
XS Rating Curve= 0 ,0
Exp/Cntr=0.3,0.1

Type RM Length L Ch R = 1 ,2579.1  ,392,387.7,383.2
XS GIS Cut Line= 3
     1834277.087      145403.275     1834409.888       145434.24
     1834542.927      145466.516
#Sta/Elev= 30
     9.7 1647.72    19.5 1647.96    29.2 1648.24      39 1648.53    48.7 1648.81
    58.4 1649.08    68.2 1649.34    77.9 1649.63    87.7 1649.82    97.4 1649.08
   107.1 1645.41   116.9 1638.93   126.6 1634.99   131.4 1634.75   136.4  1634.5
   141.4  1635.2   146.1 1635.87   155.9 1639.33   165.7 1644.28   175.5 1650.93
   185.3 1658.31     195 1665.62   204.8 1672.38   214.6 1678.14   224.4 1683.13
   234.1 1688.46   243.9 1694.61   253.7 1701.08   263.5 1707.37   273.3 1713.68
#Mann= 3 , 0 , 0
       0     .08       0   131.4    .045       0   141.4     .08       0
Bank Sta=131.4,141.4
XS Rating Curve= 0 ,0
Exp/Cntr=0.3,0.1

Type RM Length L Ch R = 1 ,2191.4  ,101.7,98.8,95.6
XS GIS Cut Line= 3
     1834180.887      145802.744     1834392.339      145807.098
      1834452.62      145829.018
#Sta/Elev= 30
    10.1 1666.32    20.1    1660    30.2 1653.82    40.3 1647.86    50.4 1642.18
    60.4 1637.05    70.5 1633.55    80.6 1632.57    90.6  1632.9   100.7 1633.15
   110.8 1631.98   120.9 1629.15   125.9 1628.33   130.9 1627.51   135.9 1627.54
     141 1627.56   151.1 1627.99   161.1 1629.04   171.2 1630.23   181.3 1631.43
   191.4  1633.8   201.4 1638.01   211.5 1642.86   220.7 1646.23   229.8 1648.64
     239 1650.43   248.1 1651.72   257.3 1652.87   266.5 1654.05   275.6 1655.29
#Mann= 3 , 0 , 0
       0     .08       0   125.9    .045       0   135.9     .08       0
Bank Sta=125.9,135.9
XS Rating Curve= 0 ,0
Exp/Cntr=0.3,0.1

Type RM Length L Ch R = 1 ,2092.6  ,319.2,326.6,334
XS GIS Cut Line= 2
     1834143.355      145905.039     1834490.281      145869.639
#Sta/Elev= 30
      10  1705.4    19.9 1697.73    29.9 1689.86    49.8 1673.59    59.8 1665.91
    69.7 1658.62    79.7  1651.8   109.6 1632.93   119.6 1627.44   124.5 1626.19
   129.5 1624.92   134.5 1625.19   139.5 1625.45   149.5 1627.81   159.4 1630.27
   169.4 1631.05   189.3 1630.49   229.2 1630.18   239.1 1630.53   249.1 1632.04
   259.1 1634.11     269    1636     279 1637.74   288.9 1639.68   298.9 1642.15
   308.9 1645.59   318.8    1650   328.8 1654.84   338.8  1658.8   348.7  1661.9
#Mann= 3 , 0 , 0
       0     .08       0   124.5    .045       0   134.5     .06       0
Bank Sta=124.5,134.5
XS Rating Curve= 0 ,0
Exp/Cntr=0.3,0.1

Type RM Length L Ch R = 1 ,1766    ,390.6,394.7,398.8
XS GIS Cut Line= 3
     1834130.781       146156.17     1834202.835      146196.596
     1834465.603      146268.857
#Sta/Elev= 25
     9.2 1694.13    27.5  1680.4    73.4 1646.67    82.6 1639.84    92.7 1631.78
   102.8 1624.05   112.9 1619.59     118 1619.29     123 1618.98     128 1619.47
   143.2 1620.98   153.3  1621.5     234 1622.15   244.1 1622.56   254.2 1623.81
   264.3 1625.63   274.4 1627.63   284.5 1629.85   294.6 1632.51   304.7 1635.49
   314.8 1638.63   324.9 1641.92     335 1645.51     345 1649.49   355.1 1653.94
#Mann= 3 , 0 , 0
     9.2     .08       0     118    .045       0     128     .06       0
#XS Ineff= 2 , 0
                          200.51         1637.64
Permanent Ineff=
       F       F
Bank Sta=118,128
XS Rating Curve= 0 ,0
Exp/Cntr=0.3,0.1

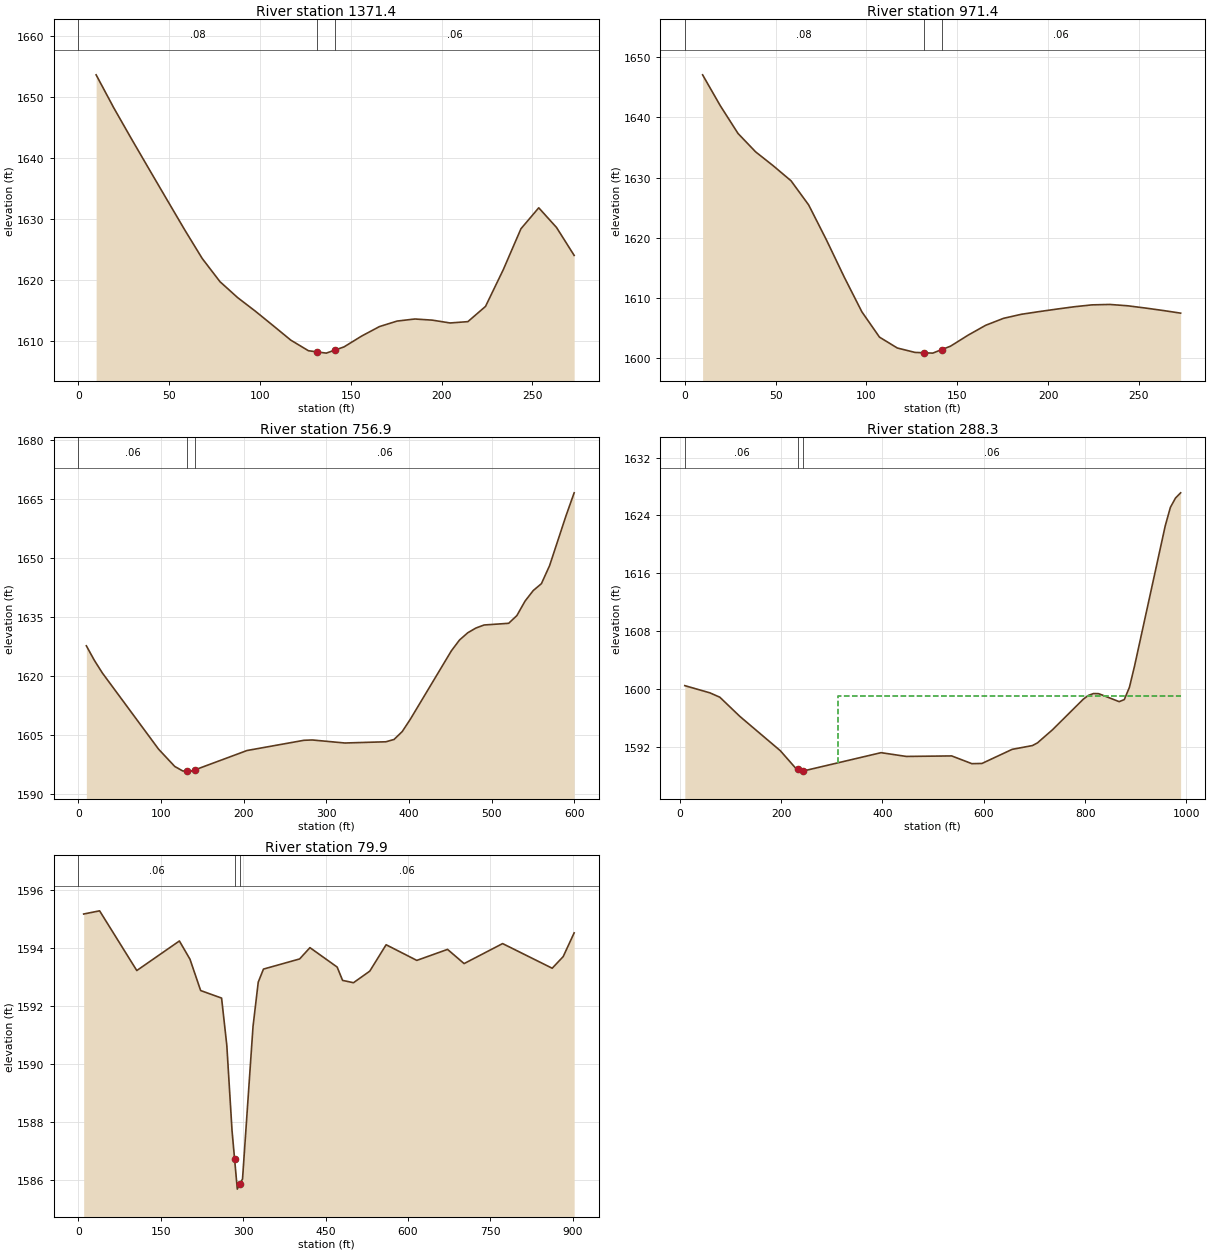
Type RM Length L Ch R = 1 ,1371.4  ,397.5,400,402.5
XS GIS Cut Line= 3
      1834016.56        146520.5     1834137.998       146582.83
     1834259.436       146645.16
#Sta/Elev= 30
     9.8 1653.58    19.5 1648.19    29.3 1643.09      39 1638.14    48.8 1633.17
    58.5 1628.27    68.2 1623.56      78 1619.76    87.7 1617.16    97.5 1614.93
   107.2 1612.59     117  1610.2   126.7 1608.47   131.5 1608.28   136.5 1608.08
   141.5  1608.6   146.3  1609.1     156 1610.87   165.8 1612.42   175.5 1613.32
   185.3 1613.66     195 1613.47   204.7 1613.01   214.5 1613.23   224.2 1615.72
     234 1621.74   243.7 1628.41   253.5 1631.84   263.3 1628.62     273 1624.06
#Mann= 3 , 0 , 0
       0     .08       0   131.5    .045       0   141.5     .06       0
Bank Sta=131.5,141.5
XS Rating Curve= 0 ,0
Exp/Cntr=0.3,0.1

Type RM Length L Ch R = 1 ,971.4   ,215.7,214.5,213.3
XS GIS Cut Line= 3
     1833826.833       146852.27     1833939.391       146929.49
     1834051.949       147006.71
#Sta/Elev= 30
     9.8 1647.03    19.5 1641.93    29.3 1637.31      39 1634.26    48.7 1631.95
    58.5 1629.46    68.2 1625.46      78 1619.65    87.8 1613.49    97.5 1607.74
   107.2 1603.54     117 1601.74   126.7 1601.01   131.5 1600.95   136.5 1600.89
   141.5 1601.48   146.3 1602.04     156 1603.87   165.7 1605.51   175.5 1606.66
   185.3 1607.33     195 1607.77   204.8 1608.19   214.5 1608.58   224.2 1608.89
     234 1608.96   243.8 1608.74   253.5 1608.37   263.3 1607.96     273 1607.52
#Mann= 3 , 0 , 0
       0     .08       0   131.5    .045       0   141.5     .06       0
Bank Sta=131.5,141.5
XS Rating Curve= 0 ,0
Exp/Cntr=0.3,0.1

Type RM Length L Ch R = 1 ,756.9   ,467.6,468.5,469.5
XS GIS Cut Line= 3
     1833689.047      147024.879      1833880.21      147140.521
     1834247.197      147223.123
#Sta/Elev= 30
     9.7 1627.71    19.4 1624.01    29.1 1620.79    97.1 1601.42   116.6 1597.04
   126.3 1595.89     131 1595.87     136 1595.85     141 1596.17     204 1601.09
   272.9 1603.69   282.8 1603.77   322.4    1603   371.9 1603.31   381.8  1603.9
   391.7 1605.91   401.6 1609.08   451.1 1626.43     461 1629.19   470.9 1631.02
   480.8 1632.23   490.7    1633   520.4 1633.43   530.3 1635.39   540.2 1639.07
   550.1 1641.75     560 1643.51   569.9  1648.1   589.7 1660.74   599.6  1666.6
#Mann= 3 , 0 , 0
       0     .06       0     131    .045       0     141     .06       0
Bank Sta=131,141
XS Rating Curve= 0 ,0
Exp/Cntr=0.3,0.1

Type RM Length L Ch R = 1 ,288.3   ,216.2,208.4,200.8
XS GIS Cut Line= 4
     1833332.028      147212.322     1833349.944      147329.588
     1833858.097      147679.758     1834110.545      147666.728
#Sta/Elev= 30
     9.9 1600.48    59.3 1599.49    79.1 1598.88   118.6 1596.23   198.3  1591.5
   228.1 1589.13   233.1  1588.9   238.1 1588.67   243.1 1588.68   397.3 1591.22
   447.1  1590.7   536.7 1590.77   576.5  1589.7   596.4 1589.73   656.1 1591.68
   695.9  1592.2   705.9 1592.57   735.7 1594.39   796.4 1598.61   806.5 1599.13
   816.6 1599.39   826.8 1599.37   867.2 1598.27   877.3 1598.55   887.4 1600.24
   897.5 1603.17   958.2 1622.58   968.3 1625.11   978.4  1626.4   988.5 1627.12
#Mann= 3 , 0 , 0
     9.9     .06       0   233.1    .045       0   243.1     .06       0
#XS Ineff= 2 , 0
                          312.08            1599
Permanent Ineff=
       F       F
Bank Sta=233.1,243.1
XS Rating Curve= 0 ,0
Exp/Cntr=0.3,0.1

Type RM Length L Ch R = 1 ,79.9    ,73.8,79.9,86
XS GIS Cut Line= 6
     1833141.913      147328.137     1833238.809      147528.497
     1833427.673      147587.619     1833539.349      147669.734
     1833611.609      147755.133     1833728.212      147953.851
#Sta/Elev= 30
     9.7 1595.17    38.7 1595.28   106.4 1593.22   183.9 1594.24   203.2 1593.61
   222.6 1592.53   260.7 1592.27   270.2 1590.64   279.7  1587.7   284.3 1586.73
   289.3 1585.68   294.3 1585.87   298.8 1586.03   317.9 1591.29   327.4 1592.82
   336.9 1593.27   402.7 1593.62   421.5 1594.01     471 1593.34   480.9 1592.88
   500.7  1592.8   530.4  1593.2   560.1 1594.11     616 1593.57   671.9 1593.95
     702 1593.46   772.1 1594.15   862.3  1593.3   882.3  1593.7   902.3 1594.52
#Mann= 3 , 0 , 0
       0     .06       0   284.3    .045       0   294.3     .06       0
Bank Sta=284.3,294.3
XS Rating Curve= 0 ,0
Exp/Cntr=0.3,0.1

Chan Stop Cuts=-1
Use User Specified Reach Order=0